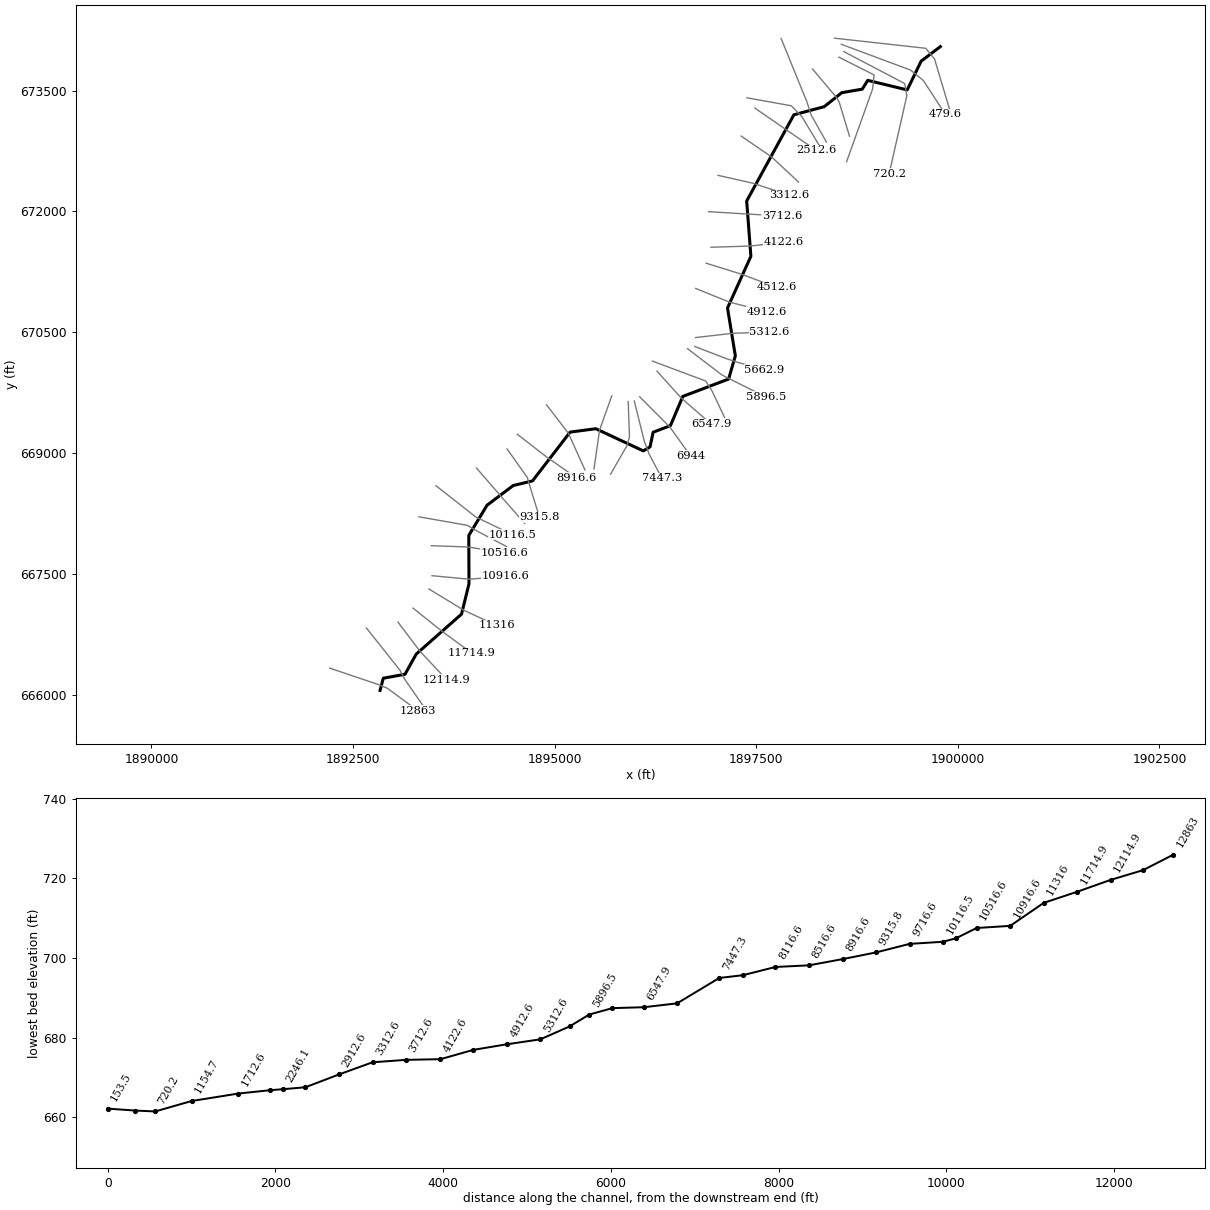
--- TriplettRn.prj (project) ---

Proj Title=TriplettRn
Current Plan=p01
Default Exp/Contr=0,0
English Units
Geom File=g01
Flow File=f01
Plan File=p01
BEGIN DESCRIPTION:
AMEC Environment & Infrastructure, 2013
Projection: NAD 1983 State Plane West Virginia South FIPS 4702 (US Feet)
Vertical Datum: NAVD 1988
END DESCRIPTION:
DSS Export Rating Curves= 0
DSS Export Rating Curve Sorted= 0
DSS Export Volume Flow Curves= 0
DXF OffsetX= 0
DXF OffsetY= 0
DXF ScaleX= 0
DXF ScaleY= 0

--- TriplettRn.p01 (plan) ---

Plan Title=Floodplain
Program Version=4.00
Geom File=g01
Flow File=f01
K Sum by GR=0
Std Step Tol=0.01
Critical Tol=0.01
Num of Std Step Trials=20
Max Error Tol=0.3
Flow Tol Ratio=0.001
Split Flow NTrial=30
Split Flow Tol=0.02
Split Flow Ratio=0.02
Log Output Level=0
Friction Slope Method=1
Unsteady Friction Slope Method=2
Unsteady Bridges Friction Slope Method=1
Global Log Level=0
CheckData=False
Run HTab=0
Run UNet=0
Run PostProcess=0
UNET Theta=0
UNET Theta Warmup=0
UNET ZTol=0
UNET ZSATol=0
UNET MxIter=0
UNET MaxInSteps=0
UNET DtIC=0
UNET DtMin=0
UNET MaxCRTS=0
UNET WFStab=0
UNET SFStab=0
UNET WFX=0
UNET SFX=0
UNET DSS MLevel=0
UNET DZMax Abort=0
UNET Convert EG Bridges=0
UNET Use Existing IB Tables=0
UNET Froude Limit=0
UNET Froude Power=0
Write IC File=0
Echo Input=False
Echo Output=False
Write Detailed=0

--- TriplettRn.f01 (steady flow) ---

Flow Title=NFF Regression Equation
Program Version=4.10
Number of Profiles= 1
Profile Names=P100yr
River Rch & RM=TriplettRn,Main            ,12863
876.6693
River Rch & RM=TriplettRn,Main            ,10269.7
970.7408
River Rch & RM=TriplettRn,Main            ,10116.5
1173.221
River Rch & RM=TriplettRn,Main            ,6172.8
1235.276
River Rch & RM=TriplettRn,Main            ,5896.5
1374.567
River Rch & RM=TriplettRn,Main            ,2246.1
1420.282
River Rch & RM=TriplettRn,Main            ,2093.1
2021.492
River Rch & RM=TriplettRn,Main            ,479.6
 2081.44
River Rch & RM=TriplettRn,Main            ,153.5
2083.424
Boundary for River Rch & Prof#=TriplettRn,Main            , 1
Up Type= 0
Dn Type= 3
Dn Slope=0.00601
DSS Import GetInterval= 0
DSS Import GetPeak= 0
DSS Import FillOption= 0

--- TriplettRn.g01 (geometry) ---

Geom Title=USGS 3m DEM
Program Version=4.10

River Reach=TriplettRn      ,Main
Reach XY= 30
     1892834.445       666057.02     1892874.802      666208.644
     1893143.521      666257.389     1893282.453       666507.49
     1893844.822      667003.888     1893937.183      667379.379
     1893934.823       667980.14     1894161.315      668355.091
     1894486.435      668599.666     1894724.615      668656.665
      1895191.06      669262.096     1895510.013      669304.302
     1896098.724      669029.252     1896182.391      669078.868
      1896220.97        669260.4     1896435.707      669343.048
      1896589.15       669705.03     1897157.235      669920.826
     1897240.423      670208.722     1897143.301      670802.393
     1897433.157      671443.581     1897381.027      672129.608
      1897966.28      673199.489     1898343.159      673300.237
      1898560.25      673473.924     1898813.818      673517.353
     1898882.601      673626.662     1899371.763      673508.141
     1899544.373      673864.526     1899782.887      674045.348

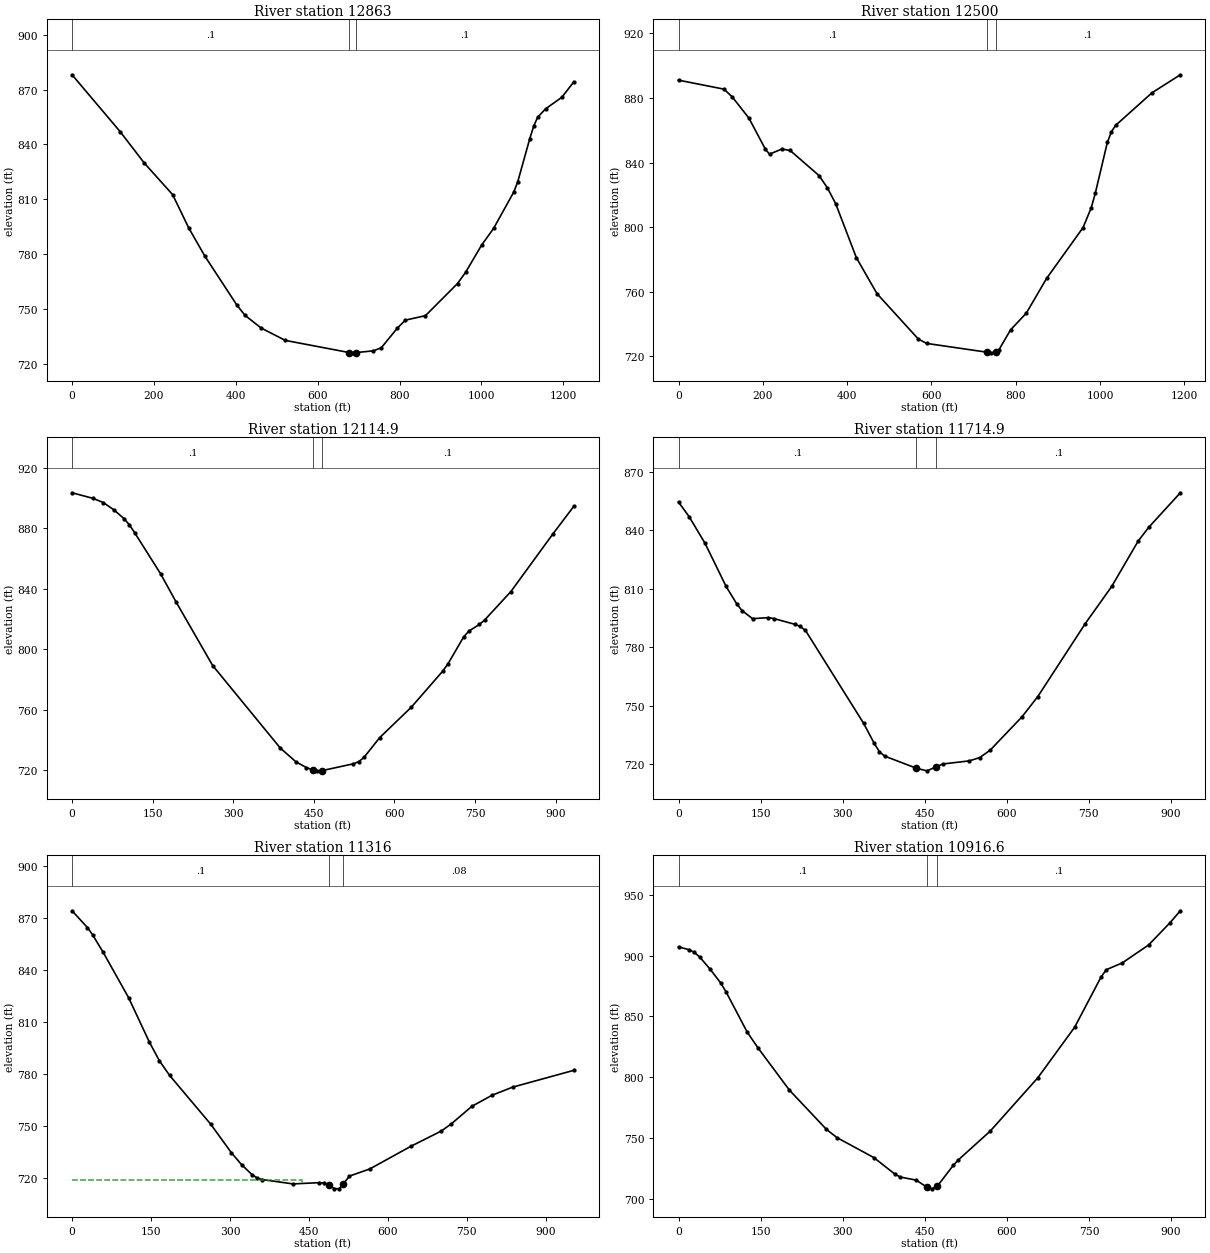
Type RM Length L Ch R = 1 ,12863   ,376.5,363,349.2
XS GIS Cut Line= 4
     1892210.382      666333.702     1892806.302      666132.313
      1892923.49       666084.57      1893302.61      665806.009
#Sta/Elev= 30
       0  878.09   117.9  846.86   176.9  829.68   245.7  812.53     285  794.34
   324.3  778.93     403     752   422.6  746.49   461.9  739.57   520.9   732.8
   677.7  726.12   687.4  725.99   693.3  726.12   736.1  727.08   755.6  728.78
   794.8  739.52   814.4  743.88   863.4  746.32   941.8  763.91   961.4     770
  1000.6  784.92    1030   794.1    1079  813.87  1088.8  819.48  1118.2  843.07
    1128  850.08  1137.8  854.96  1157.4  859.54  1196.6  865.77    1226  874.26
#Mann= 3 , 0 , 0
       0      .1       0   677.7    .045       0   693.3      .1       0
Bank Sta=677.7,693.3
XS Rating Curve= 0 ,0
Exp/Cntr=0.3,0.1

Type RM Length L Ch R = 1 ,12500   ,382.1,385.1,390.3
XS GIS Cut Line= 4
     1892664.375      666832.834     1893079.306      666310.265
     1893150.486      666180.056     1893364.797      665872.229
#Sta/Elev= 30
       0  891.06   107.9  885.49   127.6  880.63   166.8  867.62   206.1  848.27
   215.9  845.22   245.3  848.38   264.9  847.48   333.6  831.88   353.3   824.3
   372.9  814.51     422  781.03     471  758.73   569.1   730.6   588.8  727.92
   732.2  722.46   741.5  722.08   752.7  722.54     760  723.84   787.8  736.29
   825.3  746.71   873.4  768.22   959.9  799.71   979.2  811.91   988.8  820.84
  1017.6  852.55  1027.2  859.09  1036.9  862.99  1123.4  883.23  1190.7   894.4
#Mann= 3 , 0 , 0
       0      .1       0   732.2    .045       0   752.7      .1       0
Bank Sta=732.2,752.7
XS Rating Curve= 0 ,0
Exp/Cntr=0.3,0.1

Type RM Length L Ch R = 1 ,12114.9 ,394.7,400,403.9
XS GIS Cut Line= 3
     1893056.797      666904.046     1893331.792      666540.951
     1893658.806       666191.66
#Sta/Elev= 30
       0  903.48    38.8  899.81    58.2     897    77.5  892.27    96.9  886.35
   106.6   882.3   116.3  877.21   164.8   849.9   193.8  831.18   261.7  789.28
   387.6   734.7   416.7  725.61   436.1  721.83     448  720.28   455.5  719.65
   465.2  719.79   523.8  724.32   533.6  725.71   543.4  728.56   572.7  741.65
   631.2  761.63   689.8  785.51   699.6  790.32   728.9  808.21   738.7  812.08
   758.2  816.43     768  819.38   816.8  838.18   894.9  876.23     934  894.56
#Mann= 3 , 0 , 0
       0      .1       0     448    .045       0   465.2      .1       0
Bank Sta=448,465.2
XS Rating Curve= 0 ,0
Exp/Cntr=0.3,0.1

Type RM Length L Ch R = 1 ,11714.9 ,396.4,398.9,402.3
XS GIS Cut Line= 3
      1893242.86      667078.335     1893605.416      666788.583
     1893971.546      666520.424
#Sta/Elev= 30
       0  854.39    19.3  846.94    48.4   833.3      87  811.16   106.4  802.25
     116  798.82   135.4  794.64   164.4  795.17     174  794.72   212.7  791.76
   222.4  790.68   232.1  788.65   338.4  741.09   357.8  730.83   367.4  726.49
   377.1   724.2   435.1     718   454.4  716.66   471.6  718.73   483.4  720.17
   531.7  721.76     551  723.44   570.3  727.32   628.3  744.35   657.2  754.73
   744.1  792.16   792.4  811.16   840.7  834.36     860  841.42   917.9  859.15
#Mann= 3 , 0 , 0
       0      .1       0   435.1    .045       0   471.6      .1       0
Bank Sta=435.1,471.6
XS Rating Curve= 0 ,0
Exp/Cntr=0.3,0.1

Type RM Length L Ch R = 1 ,11316   ,390.2,399.4,410.2
XS GIS Cut Line= 3
     1893439.961         667316.     1893873.204      667051.616
     1894277.362      666863.655
#Sta/Elev= 30
       0  874.06    29.3  864.37      39  860.22    58.6   850.4   107.4  823.99
   146.4   798.7   165.9  787.64   185.4  779.18   263.5  751.08   302.6  734.69
   322.1  727.78   341.6  722.12   351.4  720.18   361.1  719.22   419.7  716.71
   468.5  717.41   478.3  717.26     488  716.01   497.8  714.04   507.5  713.87
     515716.6057   526.9   721.2   565.7  725.34   643.2  738.31   701.3  747.15
   720.7  751.35   759.5   761.4   798.2  767.83     837  772.46   953.3  782.15
#Mann= 3 , 0 , 0
       0      .1       0     488    .045       0     515     .08       0
#XS Ineff= 2 , 0
           436.5  719.09
Permanent Ineff=
       F       F
Bank Sta=488,515
XS Rating Curve= 0 ,0
Exp/Cntr=0.3,0.1

Type RM Length L Ch R = 1 ,10916.6 ,398.8,400,395.3
XS GIS Cut Line= 3
     1893478.632      667480.388     1893939.787      667437.392
     1894391.976      667472.646
#Sta/Elev= 30
       0  907.27    19.3  904.93      29   902.7    38.6  898.93    57.9  888.78
    77.2  877.47    86.8  870.24   125.4  837.16   144.7   824.4   202.6  789.32
   270.2  757.04   289.5  750.23     357  733.76   395.6  720.07   405.3  717.78
   434.2  715.26   453.5  709.52   463.2  708.09   472.8  710.34   501.8  727.36
   511.4  732.03   569.3  755.55   656.2  799.43   723.7  841.17     772  882.56
   781.6   888.5   810.6  894.05   858.8  908.86   897.4  926.92   916.7  936.98
#Mann= 3 , 0 , 0
       0      .1       0   453.5    .045       0   472.8      .1       0
Bank Sta=453.5,472.8
XS Rating Curve= 0 ,0
Exp/Cntr=0.3,0.1

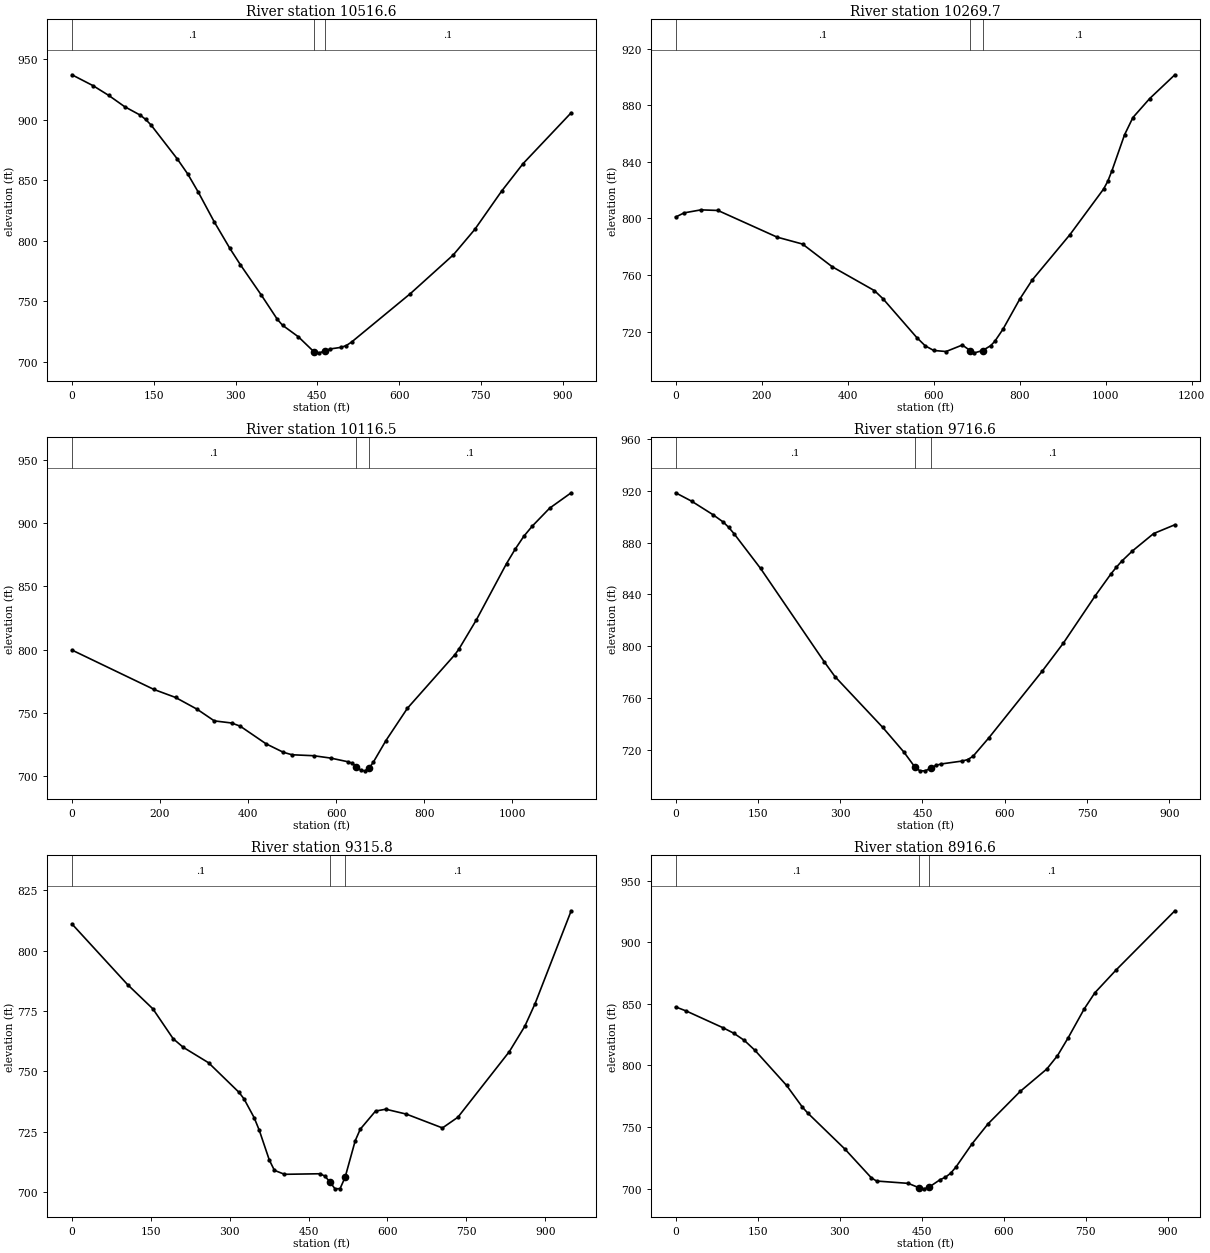
Type RM Length L Ch R = 1 ,10516.6 ,256.5,246.9,239.8
XS GIS Cut Line= 3
     1893470.942      667852.923      1893924.47      667836.745
     1894380.497      667764.542
#Sta/Elev= 30
       0  936.94    38.6  927.98    67.6  919.88    96.6  910.64   125.5  903.59
   135.2  900.07   144.8  895.65   193.1  867.57   212.4  855.06   231.7  840.11
   260.7   815.8   289.7  793.65     309  780.16   347.6     755   376.6  735.23
   386.2  730.32   415.2   720.8   444.2  708.25   453.8  707.56   463.6  709.15
   473.5  710.77   493.1  712.05   502.9  713.52   512.8  716.46   620.8  756.49
   699.4   788.4   738.7  809.36   787.8  840.88   827.1  863.57   915.5  905.61
#Mann= 3 , 0 , 0
       0      .1       0   444.2    .045       0   463.6      .1       0
Bank Sta=444.2,463.6
XS Rating Curve= 0 ,0
Exp/Cntr=0.3,0.1

Type RM Length L Ch R = 1 ,10269.7 ,151.9,153.2,154.5
XS GIS Cut Line= 4
     1893316.285      668211.306     1893916.979      668105.404
     1894047.187      668029.015     1894401.354      667843.251
#Sta/Elev= 30
       0  800.96    19.7  803.93      59  806.06    98.4  805.64   236.1  786.77
   295.1  781.89     364  765.87   462.4  748.94   482.1  743.25   560.8  715.77
   580.4  709.94   600.1  706.66   628.8  705.91   666.6   710.5   685.4  706.48
   694.9  704.98   713.7  706.58   732.6  710.06     742  713.08   760.9  721.55
   799.9  742.81   829.2  756.51     917   788.6     995  820.74  1004.8  826.24
  1014.5  833.71  1043.8  859.11  1063.3  871.35  1102.3  884.75  1160.8  901.56
#Mann= 3 , 0 , 0
       0      .1       0   685.4    .045       0   713.7      .1       0
Bank Sta=685.4,713.7
XS Rating Curve= 0 ,0
Exp/Cntr=0.3,0.1

Type RM Length L Ch R = 1 ,10116.5 ,408,399.9,391.8
XS GIS Cut Line= 4
      1893528.09      668596.723     1894021.146       668209.57
     1894107.101      668167.877     1894477.246      667989.277
#Sta/Elev= 30
       0  799.67   186.1   768.5   235.1  762.18   284.1  752.86   323.2  743.62
   362.4  741.96     382  739.44   440.8  725.46     480  718.77   499.6  716.82
   548.5  716.07   587.7  714.18   626.9  711.26   636.4  710.08     646  707.28
   655.6  704.63   665.1   704.1   674.8  706.32   684.2  710.96   712.9  728.09
   761.6  753.62   869.2  795.95     879   800.7   918.1  823.52   986.6  868.09
  1006.2  879.47  1025.8  889.67  1045.3  897.83  1084.5  911.94  1133.4  924.11
#Mann= 3 , 0 , 0
       0      .1       0     646    .045       0   674.8      .1       0
Bank Sta=646,674.8
XS Rating Curve= 0 ,0
Exp/Cntr=0.3,0.1

Type RM Length L Ch R = 1 ,9716.6  ,409.3,400.8,392.2
XS GIS Cut Line= 3
     1894029.742      668816.538     1894327.824      668472.774
     1894626.835       668129.82
#Sta/Elev= 30
       0  918.48      29  912.03    67.8  901.63    87.1  895.78    96.8  891.74
   106.5  886.87   154.9  859.97   271.1  787.74   290.4  776.45   377.6  737.11
   416.3  717.97   435.6  706.81   445.3  703.57     455  703.57   464.7  705.62
   474.4  707.75     484  708.88   522.8  711.17   532.4  712.28   542.1   714.8
   571.2   729.2     668  780.49   706.7  802.25   764.8  838.84   793.8  855.94
   803.5     861   813.2  865.63   832.6   873.5   871.3  886.96     910  893.76
#Mann= 3 , 0 , 0
       0      .1       0   435.6    .045       0   464.7      .1       0
Bank Sta=435.6,464.7
XS Rating Curve= 0 ,0
Exp/Cntr=0.3,0.1

Type RM Length L Ch R = 1 ,9315.8  ,386.7,399.2,412.7
XS GIS Cut Line= 4
     1894409.549      669053.303     1894660.035      668700.022
     1894698.279      668571.176     1894811.499      668206.412
#Sta/Elev= 30
       0     811   105.9  785.88     154  775.86   192.5  763.51   211.7  759.96
   259.8  753.57   317.6  741.36   327.2  738.64   346.5  730.86   356.1  725.74
   375.3  713.36     385  709.08   404.2  707.43   471.5  707.66   481.1   706.7
   490.7   704.2   500.3  701.42   509.9  701.52   519.5  706.22   538.7  721.32
   548.3   726.1   577.3  733.58   596.8  734.36     636  732.33   704.6  726.61
     734  731.05   831.9  758.22   861.3  768.72   880.8  778.07   949.4  816.44
#Mann= 3 , 0 , 0
       0      .1       0   490.7    .045       0   519.5      .1       0
Bank Sta=490.7,519.5
XS Rating Curve= 0 ,0
Exp/Cntr=0.3,0.1

Type RM Length L Ch R = 1 ,8916.6  ,405.2,400,389.2
XS GIS Cut Line= 3
     1894537.585      669234.925     1894896.257       668955.98
     1895272.145      668693.349
#Sta/Elev= 30
       0  847.44    19.3  844.16      87  830.46   106.3  826.09   125.7  820.25
     145  812.24     203  783.66     232  765.98   241.7  761.23   309.4  732.11
   357.7  708.79   367.4  706.09   425.4  704.18   444.7  700.69   454.4  699.74
   464.1  701.33   483.6  707.16   493.4  709.17   503.2  712.52   512.9  717.62
   542.2  736.36   571.4  752.56     630   778.8   678.8  797.04   698.3  807.87
   717.8  822.36   747.1  845.76   766.6   858.9   805.6  877.49   912.9  925.49
#Mann= 3 , 0 , 0
       0      .1       0   444.7    .045       0   464.1      .1       0
Bank Sta=444.7,464.1
XS Rating Curve= 0 ,0
Exp/Cntr=0.3,0.1

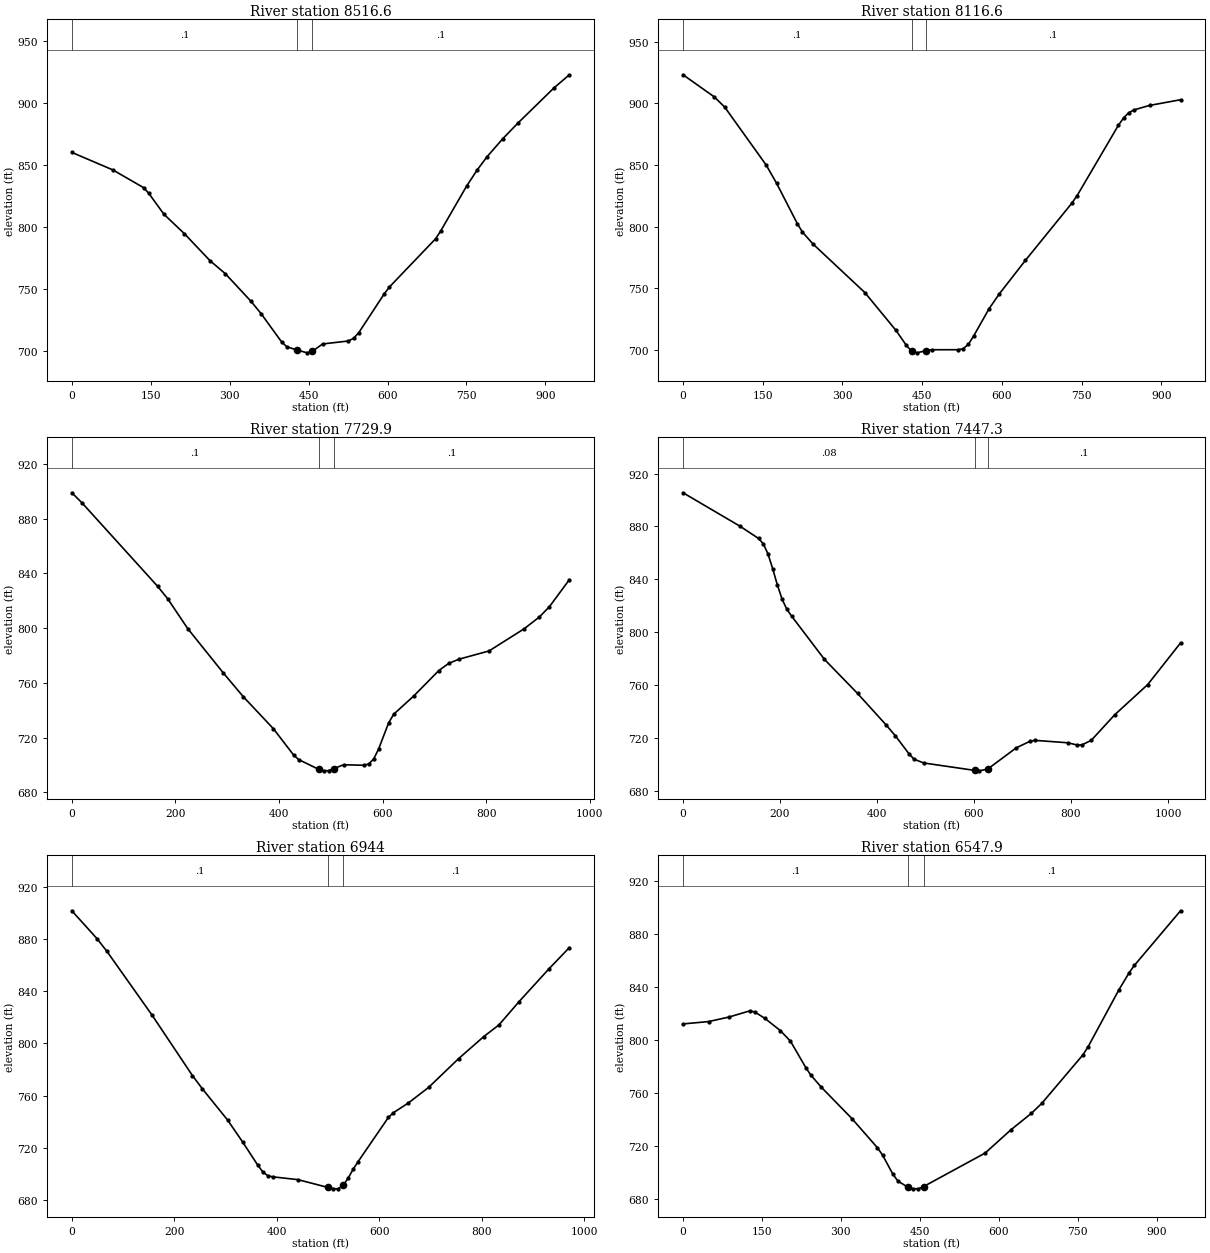
Type RM Length L Ch R = 1 ,8516.6  ,420.1,400,388.6
XS GIS Cut Line= 3
      1894898.69      669601.721     1895170.467      669246.347
     1895375.497      668792.346
#Sta/Elev= 30
       0  859.82    77.8  845.72   136.2  831.44   145.9  827.01   175.1  809.92
     214  794.23   262.6  772.51   291.8  761.97   340.4  739.79   359.8  729.72
   398.8  706.89   408.5   703.1   427.9  700.44   447.4  698.18   457.2  699.46
   476.7  705.34   525.5  707.73   535.3  709.81   545.1   714.3   593.9  745.87
   603.7  751.33   691.6   790.3   701.3  796.65   750.2  832.62   769.7  845.25
   789.2  856.37   818.6  870.67   847.9  883.51   916.2  911.78   945.5  922.43
#Mann= 3 , 0 , 0
       0      .1       0   427.9    .045       0   457.2      .1       0
Bank Sta=427.9,457.2
XS Rating Curve= 0 ,0
Exp/Cntr=0.3,0.1

Type RM Length L Ch R = 1 ,8116.6  ,385.4,386.7,384
XS GIS Cut Line= 3
     1895707.509      669711.346     1895556.968      669287.895
     1895487.515      668806.221
#Sta/Elev= 30
       0  923.23    58.6  905.34    78.2   897.1   156.3   850.1   175.9  835.32
   214.9  802.61   224.7  795.66   244.2  786.13     342  746.67   400.6  715.98
   420.1  703.87   429.9   699.1   439.6  697.77   456.9  699.47   468.9  700.28
   517.6   700.3   527.3  701.13     537  704.76   546.7  711.36   575.9  733.61
   595.4  745.75   644.1  772.69   731.7  819.21   741.4  825.18   819.3  882.37
     829   888.3   838.7  892.49   848.5  894.77   877.7  898.37   936.1  902.99
#Mann= 3 , 0 , 0
       0      .1       0   429.9    .045       0   456.9      .1       0
Bank Sta=429.9,456.9
XS Rating Curve= 0 ,0
Exp/Cntr=0.3,0.1

Type RM Length L Ch R = 1 ,7729.9  ,269.6,282.6,295.4
XS GIS Cut Line= 4
     1895911.864      669641.489     1895927.396      669203.928
     1895895.639      669092.793     1895692.804      668740.152
#Sta/Elev= 30
       0  898.82    19.5   891.5   165.4  830.56   184.9  821.45   223.8  799.54
   291.9  767.42   330.8  749.89   389.2   726.4   428.1   707.2   437.8  703.92
   476.4  696.82     486   695.7   495.6  695.84   506.2  697.39   524.5  700.14
   563.1  699.78   572.8  700.64   582.5  704.31   592.2  711.76   611.5  730.77
   621.2  737.06     660  750.41   708.4  768.99   727.8  774.28   747.1  777.23
   805.3  783.29   873.1   799.5   902.1     808   921.5  815.47   960.2   835.3
#Mann= 3 , 0 , 0
       0      .1       0   476.4    .045       0   506.2      .1       0
Bank Sta=476.4,506.2
XS Rating Curve= 0 ,0
Exp/Cntr=0.3,0.1

Type RM Length L Ch R = 1 ,7447.3  ,494.3,503.3,505.9
XS GIS Cut Line= 4
     1895987.349      669647.479     1896111.858      669147.504
     1896172.622      668986.914     1896331.042      668687.435
#Sta/Elev= 30
       0  905.43   116.7  880.28   155.6  870.87   165.3  866.88     175  859.25
   184.7  848.11   194.4  835.71   204.2  824.95   213.9  817.31   223.6  812.21
   291.6  779.33   359.7  753.61     418  730.02   437.5  721.64   466.6  707.54
   476.4  703.83   495.8  700.99   601.1  695.36   610.6  695.01   628.1  696.34
     687  712.41     716  717.48   725.7  718.08   793.4  716.25   812.8  714.54
   822.5  714.65   841.8  718.13   890.2  737.48     958  760.26  1025.8   791.8
#Mann= 3 , 0 , 0
       0     .08       0   601.1    .045       0   628.1      .1       0
Bank Sta=601.1,628.1
XS Rating Curve= 0 ,0
Exp/Cntr=0.3,0.1

Type RM Length L Ch R = 1 ,6944    ,397.1,396.1,399.5
XS GIS Cut Line= 3
      1896054.28      669700.294      1896428.08      669325.039
      1896685.39      668965.964
#Sta/Elev= 30
       0  901.48      49  880.19    68.7  870.31   156.9  821.44   235.4  775.37
     255  765.11   304.1  741.31   333.5  724.48   362.9  706.84   372.7  701.67
   382.5   698.7   392.3  697.82   441.4  695.67   500.2   689.7     510  688.76
   519.8  688.63   529.7  691.28   539.5  696.81   549.3  703.63   559.1  709.55
     618  743.25   627.8  746.88   657.3  754.41   696.6  766.26   755.4  788.38
   804.5  805.24     834  814.12   873.2  831.91   932.2  857.28   971.4  873.28
#Mann= 3 , 0 , 0
       0      .1       0   500.2    .045       0   529.7      .1       0
Bank Sta=500.2,529.7
XS Rating Curve= 0 ,0
Exp/Cntr=0.3,0.1

Type RM Length L Ch R = 1 ,6547.9  ,378.6,375.1,369.3
XS GIS Cut Line= 3
     1896268.465      670018.158      1896568.61      669686.445
     1896943.902      669358.544
#Sta/Elev= 30
       0  812.05    48.6  813.83    87.5  817.26   126.4  821.85   136.2   821.1
   155.6   816.2   184.8  807.06   204.2  799.02   233.4  779.04   243.1  773.31
   262.6  764.42   320.9  740.68   369.6   718.6   379.3  713.06   398.7  698.84
   408.4  693.52   427.9  688.77   437.6  687.66   447.4  687.76   457.1  689.36
   574.4  714.69   623.2  732.17   662.3  744.67   681.9  752.13     760  788.65
   769.8   794.7   828.4  837.69     848  850.64   857.8  856.15   945.7  897.39
#Mann= 3 , 0 , 0
       0      .1       0   427.9    .045       0   457.1      .1       0
Bank Sta=427.9,457.1
XS Rating Curve= 0 ,0
Exp/Cntr=0.3,0.1

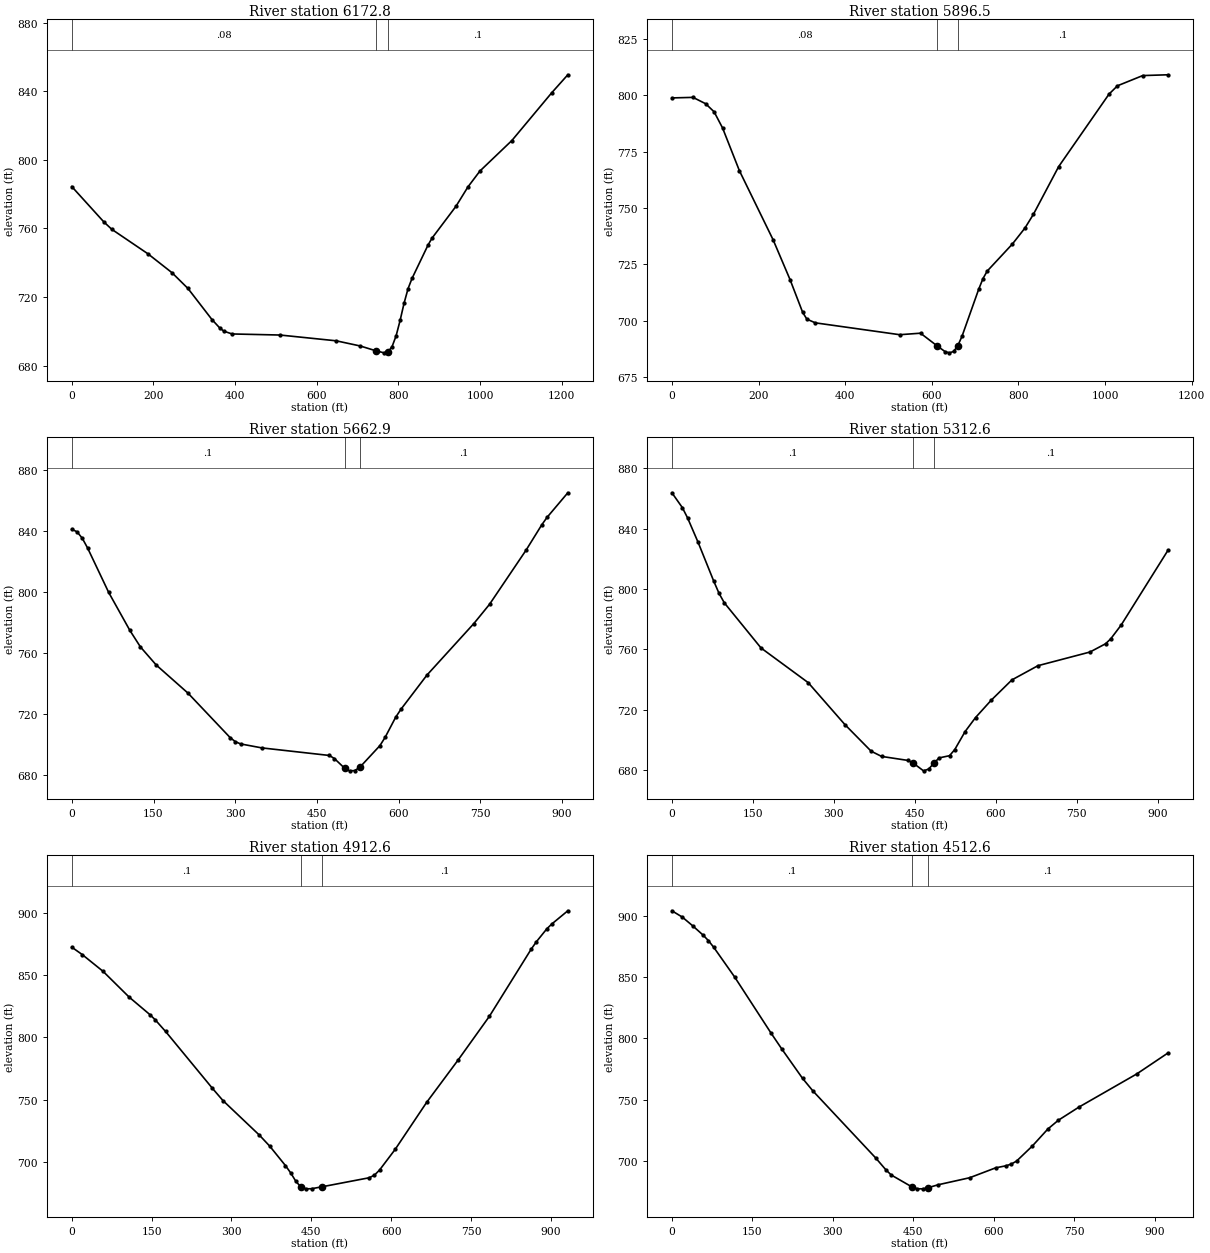
Type RM Length L Ch R = 1 ,6172.8  ,264.9,276.3,287.6
XS GIS Cut Line= 4
      1896211.25      670143.598     1896873.142      669896.202
     1896951.267      669772.504     1897106.292       669445.33
#Sta/Elev= 30
       0  784.46    78.5  763.84    98.1   759.5   186.5  745.23   245.4  734.21
   284.6  724.99   343.5  706.81   363.1  701.78   372.9  700.04   392.6  698.45
   510.3  697.82   647.7  694.45   706.6  691.43   745.6  688.57   765.1  687.43
   774.9  688.05   784.6   691.1   794.4  697.34   804.2  706.33   813.9  716.39
   823.7   724.9   833.4  730.85   872.5  750.28   882.3  754.34     941  772.93
   970.3  784.24   999.7  793.52    1078  811.34  1175.8  839.26    1215   849.7
#Mann= 3 , 0 , 0
       0     .08       0   745.6    .045       0   774.9      .1       0
Bank Sta=745.6,774.9
XS Rating Curve= 0 ,0
Exp/Cntr=0.3,0.1

Type RM Length L Ch R = 1 ,5896.5  ,230.5,233.6,236.8
XS GIS Cut Line= 4
     1896647.448      670297.678     1897072.795      669972.157
     1897192.153      669911.393       1897617.5       669698.72
#Sta/Elev= 30
       0  798.85    48.7  799.09    77.9  796.27    97.4  792.69   116.9  785.54
   155.8  766.58   233.7  735.91   272.7   718.3   301.9  703.74   311.6  700.75
   331.1  699.12   525.9  693.86   573.9  694.53   612.2  688.91   631.3  686.27
   640.8  685.82   650.4  686.44     660  689.01   669.6  693.11   708.4  714.12
   718.1  718.73   727.8  722.06     786  734.07   815.1  741.18   834.5  747.24
   892.8  768.39  1009.2  800.57  1028.6  804.23  1086.9  808.76  1145.1  809.11
#Mann= 3 , 0 , 0
       0     .08       0   612.2    .045       0     660      .1       0
Bank Sta=612.2,660
XS Rating Curve= 0 ,0
Exp/Cntr=0.3,0.1

Type RM Length L Ch R = 1 ,5662.9  ,341.6,350.3,357.3
XS GIS Cut Line= 4
     1896737.491       670323.98     1897135.729       670171.81
     1897268.108      670128.407     1897600.139      670035.091
#Sta/Elev= 30
       0  841.06     9.7  839.38    19.4  835.09    29.1  828.73    67.8  799.64
   106.6  774.83     126     764     155  752.15   213.2  733.77   290.7   704.6
   300.4   701.9     310  700.46   348.8  697.87   472.8  692.91     482   690.9
   500.6  684.63   509.9  682.84   519.2  683.01   528.5   685.1   565.6  699.35
   575.2   704.8   594.4  717.87     604  723.07   651.9  745.54   738.1  779.33
   766.8   791.9   833.9  827.39   862.6  843.91   872.2  848.77   910.5  864.95
#Mann= 3 , 0 , 0
       0      .1       0   500.6    .045       0   528.5      .1       0
Bank Sta=500.6,528.5
XS Rating Curve= 0 ,0
Exp/Cntr=0.3,0.1

Type RM Length L Ch R = 1 ,5312.6  ,410,400,394.4
XS GIS Cut Line= 3
     1896747.721      670435.447     1897210.887      670488.708
     1897663.555      670503.536
#Sta/Elev= 30
       0  863.71    19.4  853.85    29.1  847.01    48.6  830.84    77.7  805.03
    87.4  797.05    97.1  790.84   165.1  760.95   252.5     738   320.5  710.23
   369.1  692.61   388.5  689.14   437.1   686.5   446.8   684.8   466.2  679.59
   475.8  680.78   485.5  684.71   495.1  688.16   514.4  689.62     524  693.62
   543.3  705.62   562.6  714.88   591.5  726.31     630  739.81   678.2  749.21
   774.6  758.26   803.5  763.73   813.1     767   832.4  776.12   919.1  825.59
#Mann= 3 , 0 , 0
       0      .1       0   446.8    .045       0   485.5      .1       0
Bank Sta=446.8,485.5
XS Rating Curve= 0 ,0
Exp/Cntr=0.3,0.1

Type RM Length L Ch R = 1 ,4912.6  ,398.3,400,397.7
XS GIS Cut Line= 3
      1896749.03       671044.54     1897166.397      670875.357
     1897632.547      670755.423
#Sta/Elev= 30
       0  872.28    19.6  866.37    58.7  852.92   107.7  832.24   146.8  818.14
   156.6  814.06   176.2  804.64   264.3  758.94   283.9  749.21   352.4  721.44
     372  712.52   401.4  696.98   411.2  691.14     421  684.31   430.8  679.66
   440.6  678.35   450.4  678.45     470     680   558.4  687.22   568.2  689.24
     578  693.39   607.5  710.07   666.5  747.72   725.4   781.6   784.3  816.75
   862.9  870.69   872.8  876.72   892.4  887.09   902.2   891.1   931.7   901.5
#Mann= 3 , 0 , 0
       0      .1       0   430.8    .045       0     470      .1       0
Bank Sta=430.8,470
XS Rating Curve= 0 ,0
Exp/Cntr=0.3,0.1

Type RM Length L Ch R = 1 ,4512.6  ,382.5,390,398.8
XS GIS Cut Line= 3
     1896877.099      671358.367     1897314.116      671222.239
     1897751.699      671058.606
#Sta/Elev= 30
       0  904.43    19.5  899.23      39  892.03    58.4  884.43    68.2  879.94
    77.9   874.6   116.9  850.29     185  804.25   204.5   791.6   243.5  767.37
     263  756.98   379.8  702.28   399.3  692.33     409  688.25     448   678.4
   457.7  676.98   467.5  676.94   477.2  677.82   496.7   680.3   555.1  686.01
   603.7  694.13   623.2  695.82   632.9  697.25   642.6  699.63   671.8  711.87
     701  725.89   720.5  733.05   759.4  743.94   866.5  770.88   924.9  788.08
#Mann= 3 , 0 , 0
       0      .1       0     448    .045       0   477.2      .1       0
Bank Sta=448,477.2
XS Rating Curve= 0 ,0
Exp/Cntr=0.3,0.1

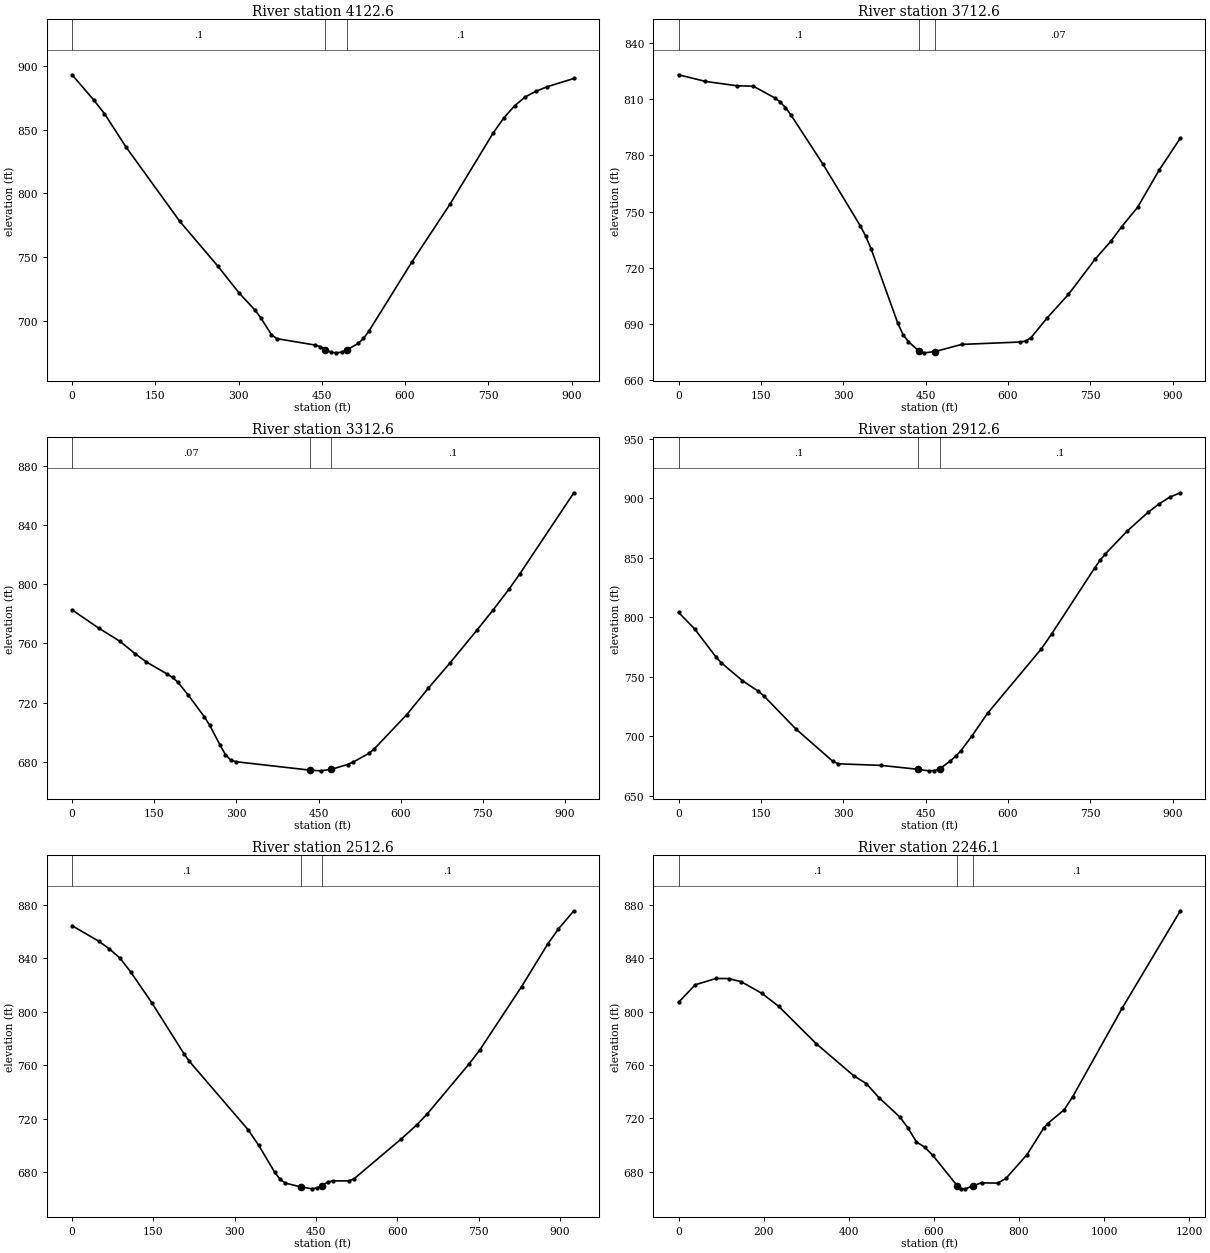
Type RM Length L Ch R = 1 ,4122.6  ,412.6,410,407.5
XS GIS Cut Line= 4
     1896937.453      671555.854     1897364.462      671568.945
     1897481.649      671576.758      1897838.42      671621.029
#Sta/Elev= 30
       0  893.18    38.8  873.48    58.3  862.67    97.1  836.45   194.2  777.91
   262.2  743.01     301  721.66   330.1  707.98   339.8   702.3   359.2  688.97
     369  685.75     437  680.81   446.8  679.56   456.6  677.16   466.4  675.13
   476.2  674.61   485.9  675.16   495.7  676.98   515.3  681.97   525.1   685.9
   534.9  691.73   612.7   746.3   680.7  791.28   758.4  847.13   777.8  859.15
   797.3  868.77   816.7  875.83   836.2  880.26   855.6  883.73   904.2  890.27
#Mann= 3 , 0 , 0
       0      .1       0   456.6    .045       0   495.7      .1       0
Bank Sta=456.6,495.7
XS Rating Curve= 0 ,0
Exp/Cntr=0.3,0.1

Type RM Length L Ch R = 1 ,3712.6  ,403.2,400,394.7
XS GIS Cut Line= 3
     1896907.378      671997.367     1897364.138      671969.519
     1897819.584      671943.715
#Sta/Elev= 30
       0  823.13    48.7   819.6   107.1  817.22   136.3  817.02   175.2  810.77
     185  808.63   194.7  805.58   204.5  801.73   262.9  775.39     331  742.37
   340.8  736.83   350.5  730.18   399.2  690.33   408.9  684.17   418.7  680.42
   438.1  675.29   447.9  674.44   467.3  675.14   515.8  678.95   622.6  680.23
   632.3  680.73     642  682.59   671.1  693.05     710   705.7   758.5  724.47
   787.6   734.2     807   741.9   836.1  752.33     875  772.03   913.8  789.24
#Mann= 3 , 0 , 0
       0      .1       0   438.1    .045       0   467.3     .07       0
Bank Sta=438.1,467.3
XS Rating Curve= 0 ,0
Exp/Cntr=0.3,0.1

Type RM Length L Ch R = 1 ,3312.6  ,407.6,400,391.4
XS GIS Cut Line= 3
     1897024.726      672448.511     1897467.121      672347.985
     1897905.763      672201.296
#Sta/Elev= 30
       0  782.72    48.3  770.43    86.9  761.59   115.8  752.88   135.1  747.62
   173.8  739.29   183.4     737     193  733.85   212.4  724.96   241.3  710.49
     251  704.79   270.3  691.18   279.9  684.86   289.6  681.07   299.2     680
   434.4   674.3   453.7  673.83   473.4  674.85   502.9  678.09   512.7  679.68
   542.2  685.68   552.1   688.8   611.1  711.86   650.5  729.75   689.8   746.7
   739.1  768.93   768.6  782.59   798.1  796.85   817.8  807.23   916.2  861.91
#Mann= 3 , 0 , 0
       0     .07       0   434.4    .045       0   473.4      .1       0
Bank Sta=434.4,473.4
XS Rating Curve= 0 ,0
Exp/Cntr=0.3,0.1

Type RM Length L Ch R = 1 ,2912.6  ,399.9,400,403.2
XS GIS Cut Line= 3
     1897313.013      672935.151     1897688.884      672677.278
     1898023.998      672365.067
#Sta/Elev= 30
       0  803.88    29.1  790.14    67.9  766.62    77.6  761.68   116.4  746.55
   145.5  737.59   155.2  733.84   213.4  706.08   281.2  678.68     291  676.69
   368.5  675.37   436.4  672.06   455.8  670.78   465.6  670.96   475.3  672.39
   494.8  679.02   504.6  682.94   514.3  687.73   533.8  699.76     563  719.31
   660.5  773.16     680  786.16   757.9  841.32   767.7  847.74   777.4  853.09
   816.4  871.99   855.4  888.16   874.9  894.97   894.4  900.72   913.8  904.42
#Mann= 3 , 0 , 0
       0      .1       0   436.4    .045       0   475.3      .1       0
Bank Sta=436.4,475.3
XS Rating Curve= 0 ,0
Exp/Cntr=0.3,0.1

Type RM Length L Ch R = 1 ,2512.6  ,270.3,266.5,262.7
XS GIS Cut Line= 3
     1897482.515      673282.818     1897854.636      673025.153
     1898244.743      672757.686
#Sta/Elev= 30
       0  864.23    49.2  852.64    68.9   846.9    88.6   839.9   108.2  829.63
   147.6  806.36   206.6   768.4   216.5   762.8   324.7  711.74   344.4     700
   373.9  679.87   383.7  674.65   393.6  671.81   423.1  668.92   442.8  667.56
   452.6  668.29   460.1  669.95   471.9  672.72   481.6  673.54   510.5  673.48
   520.2  675.08   607.1  704.83     636  715.45   655.3  723.61   732.6  761.07
   751.9  771.22   829.1  818.68   877.4  850.55   896.6  861.55   925.6  875.39
#Mann= 3 , 0 , 0
       0      .1       0   423.1    .045       0   460.1      .1       0
Bank Sta=423.1,460.1
XS Rating Curve= 0 ,0
Exp/Cntr=0.3,0.1

Type RM Length L Ch R = 1 ,2246.1  ,162.3,153,143.7
XS GIS Cut Line= 4
     1897384.427      673410.091     1897934.774      673311.133
     1898067.587      673173.112     1898288.941      672805.925
#Sta/Elev= 30
       0  806.86    39.2  820.03    88.3  824.79   117.7  824.67   147.2  822.38
   196.2  813.56   235.4  803.88   323.7  775.88     412  751.79   441.4  745.94
   470.9  735.51   519.9  720.98   539.6  712.64   559.2  702.21   578.3  698.37
   597.5  692.26     655  669.44   664.5  667.22   674.1  667.07   693.2  669.52
   712.4  671.59   750.7  671.37   770.2  675.08   818.9  692.65   857.9  712.35
   867.6  715.99   906.6  726.37   926.1  735.92    1043  802.61  1179.5  875.51
#Mann= 3 , 0 , 0
       0      .1       0     655    .045       0   693.2      .1       0
Bank Sta=655,693.2
XS Rating Curve= 0 ,0
Exp/Cntr=0.3,0.1

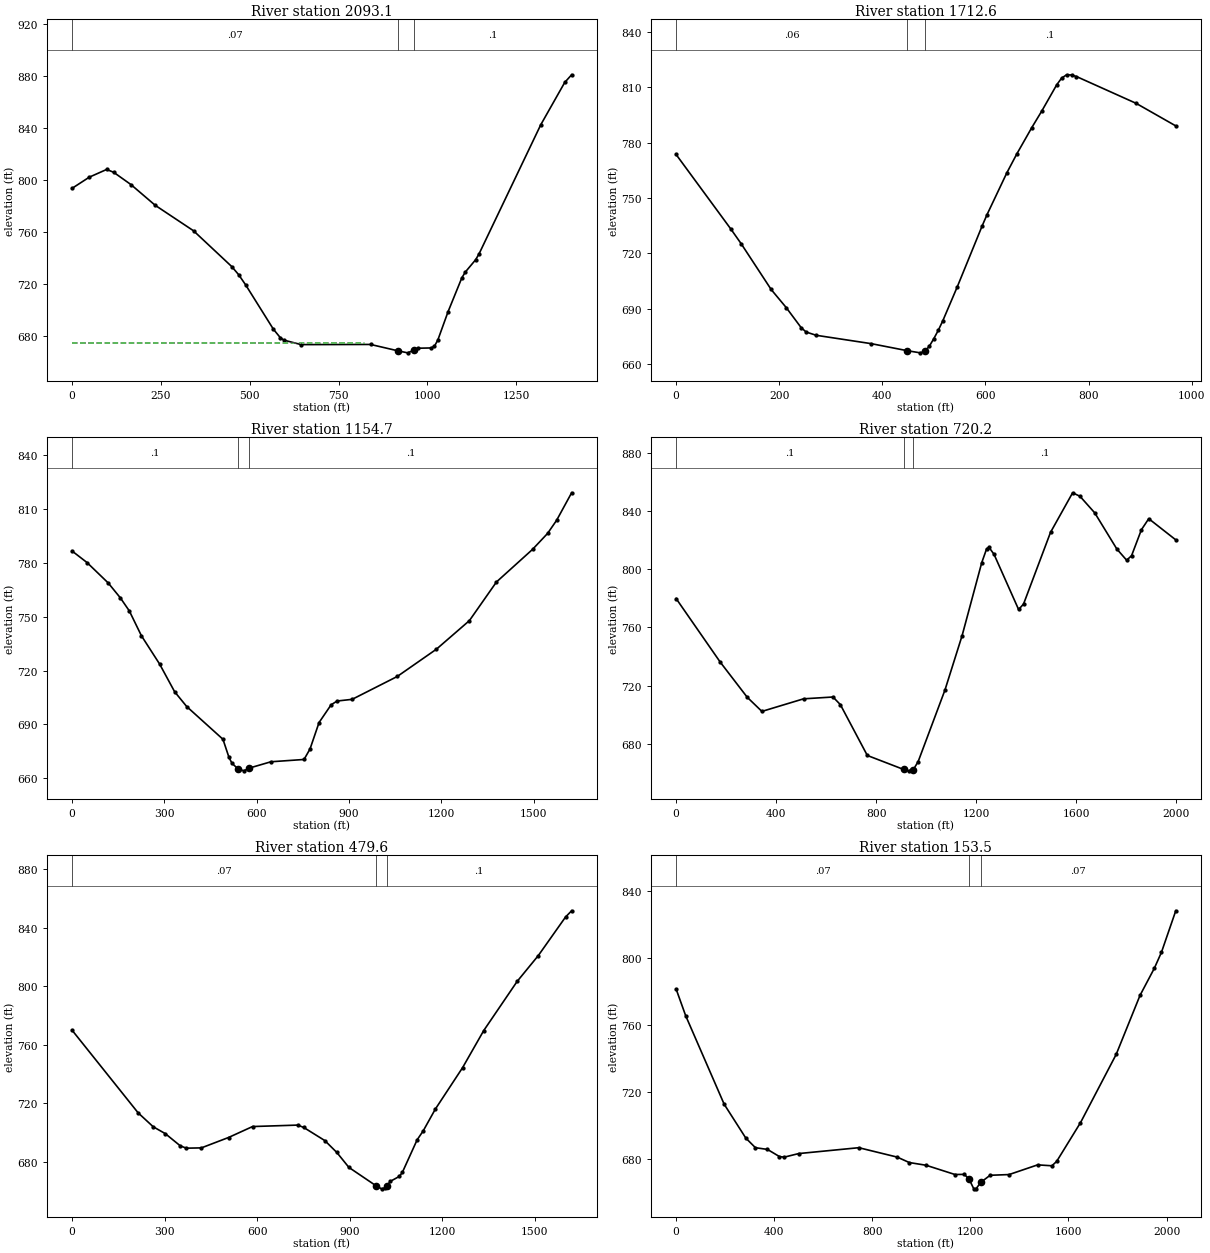
Type RM Length L Ch R = 1 ,2093.1  ,372.8,380.5,384.9
XS GIS Cut Line= 4
     1897808.038      674146.202     1898128.351      673358.702
     1898180.434      673197.244      1898369.67      672860.612
#Sta/Elev= 30
       0  793.51    48.9   802.2    97.7  808.13   117.3  805.94   166.1  796.44
   234.5  780.45     342  760.88   449.5  733.32     469  727.05   488.6  719.24
   566.8  685.02   586.3   678.5   596.1  676.63   644.9  673.16   840.4  673.28
   916.1  668.44   944.4  666.82   963.2  668.94   972.7  670.37  1010.4  670.59
  1019.8  671.86  1029.5  676.69  1058.4   698.6    1097  724.58  1106.7  729.03
  1135.6  738.47  1145.3  742.97  1319.1  842.54  1386.7  875.23    1406  881.07
#Mann= 3 , 0 , 0
       0     .07       0   916.1    .045       0   963.2      .1       0
#XS Ineff= 2 , 0
          821.55  674.59
Permanent Ineff=
       F       F
Bank Sta=916.1,963.2
XS Rating Curve= 0 ,0
Exp/Cntr=0.3,0.1

Type RM Length L Ch R = 1 ,1712.6  ,574.2,557.9,545.3
XS GIS Cut Line= 4
     1898198.406      673766.874     1898491.951      673417.777
      1898527.92      673357.646     1898656.128      672933.529
#Sta/Elev= 30
       0  773.54   106.8  732.88   126.2  725.16   184.4  700.33   213.5  690.56
   242.6  679.63   252.3  677.26   271.7   675.5   378.5  670.96   448.6  667.13
   473.6  665.98   482.4  666.82   491.1  669.52   499.9  673.68   508.7  678.27
   517.4  683.41   545.4  701.78   593.6  734.78   603.2  740.98   641.8  763.74
     661  773.91   689.9  788.11   709.2  797.05   738.1  811.24   747.7  814.94
   757.4  816.76     767  816.64   776.6  815.81   892.2  801.29   969.2  789.04
#Mann= 3 , 0 , 0
       0     .06       0   448.6    .045       0   482.4      .1       0
Bank Sta=448.6,482.4
XS Rating Curve= 0 ,0
Exp/Cntr=0.3,0.1

Type RM Length L Ch R = 1 ,1154.7  ,429,434.5,439.5
XS GIS Cut Line= 4
     1898523.316        673915.3     1898960.816      673693.945
     1898942.587      673519.466     1898620.538      672618.425
#Sta/Elev= 30
       0  786.74      49  780.25   117.7  768.88   156.9  760.62   186.3  753.28
   225.5  739.45   284.4  723.72   333.4  708.21   372.6  699.96   490.3  681.71
   509.8  671.64   519.6  668.31     539  665.23   558.5   664.1   575.7665.6318
   646.2  669.16   753.6  670.44   773.1  676.31   802.4  691.05   841.5  700.91
     861  703.04   909.8  703.97  1056.3  716.72  1183.2   731.9  1290.6  747.87
  1378.5  769.43  1495.7  787.61  1544.5   796.5  1573.8  803.81  1622.6  819.17
#Mann= 3 , 0 , 0
       0      .1       0     539    .045       0   575.7      .1       0
Bank Sta=539,575.7
XS Rating Curve= 0 ,0
Exp/Cntr=0.3,0.1

Type RM Length L Ch R = 1 ,720.2   ,226.2,240.6,255.1
XS GIS Cut Line= 4
     1898585.816      673983.008     1899341.024      673587.175
     1899367.066      673436.133     1899148.316      672469.119
#Sta/Elev= 30
       0   779.8   176.4  736.14   284.2  712.03     343  702.29   509.6  710.93
   627.2  712.18   656.6  706.95   764.4  672.04   910.1   662.4   929.3  661.48
   948.4  662.34   967.6  667.82  1074.6   716.9  1143.4  754.39  1221.9   804.5
  1241.5  814.01  1251.3  814.84    1271  810.12  1369.1  772.28  1388.8  775.97
  1496.7  825.21  1585.1  852.41  1614.5  849.99  1673.4  838.64  1761.8  813.81
    1801  806.11  1820.7  809.21    1860  827.03  1889.4  834.61  1997.4  820.08
#Mann= 3 , 0 , 0
       0      .1       0   910.1    .045       0   948.4      .1       0
Bank Sta=910.1,948.4
XS Rating Curve= 0 ,0
Exp/Cntr=0.3,0.1

Type RM Length L Ch R = 1 ,479.6   ,330.1,326.1,322.1
XS GIS Cut Line= 4
     1898554.566      674074.154     1899413.941      673753.841
     1899570.568      673626.769     1899843.628      673206.966
#Sta/Elev= 30
       0  770.06   214.6  713.54   263.4  704.06   302.5  699.38   351.2  691.03
   370.8  689.46   419.5  689.66   507.4  696.74   585.4  704.22   731.8  705.21
   751.3  703.59   819.6  694.64   858.6  686.52   897.6  676.34   984.4  663.98
  1003.6  661.71  1013.2  662.26  1020.7663.9319  1032.4  666.89  1061.2   670.2
  1070.8  672.89  1118.8  695.15  1138.5  701.27  1177.7  716.08  1266.1   744.4
  1334.8  769.76  1442.9  803.24  1511.6   820.9    1600  847.24  1619.6  851.46
#Mann= 3 , 0 , 0
       0     .07       0   984.4    .045       0  1020.7      .1       0
Bank Sta=984.4,1020.7
XS Rating Curve= 0 ,0
Exp/Cntr=0.3,0.1

Type RM Length L Ch R = 1 ,153.5   ,154.4,153.5,152.6
XS GIS Cut Line= 4
     1898471.233      674149.675     1899601.441      674024.675
     1899710.816      673891.862     1899919.149      673193.945
#Sta/Elev= 30
       0  781.64    39.2  765.62     196  712.77   284.3  692.52   323.5  686.78
   372.5  685.75   421.5  681.47   441.1  681.14   499.9  683.27     745  686.78
   901.8  681.15   950.8  677.91  1019.5  676.28  1137.1  670.76  1175.3  670.83
  1194.4  668.05  1213.6   662.3  1223.1  662.19  1242.2  666.06  1280.5   670.3
  1357.7  670.72  1474.2  676.52  1532.5  675.97  1551.9  678.61    1649  701.74
  1794.7  742.61  1891.8  777.85  1950.1  794.03  1979.2  803.61  2037.5  828.39
#Mann= 3 , 0 , 0
       0     .07       0  1194.4    .045       0  1242.2     .07       0
Bank Sta=1194.4,1242.2
XS Rating Curve= 0 ,0
Exp/Cntr=0.3,0.1

Chan Stop Cuts=-1
Use User Specified Reach Order=0
Composite Channel Slope=5